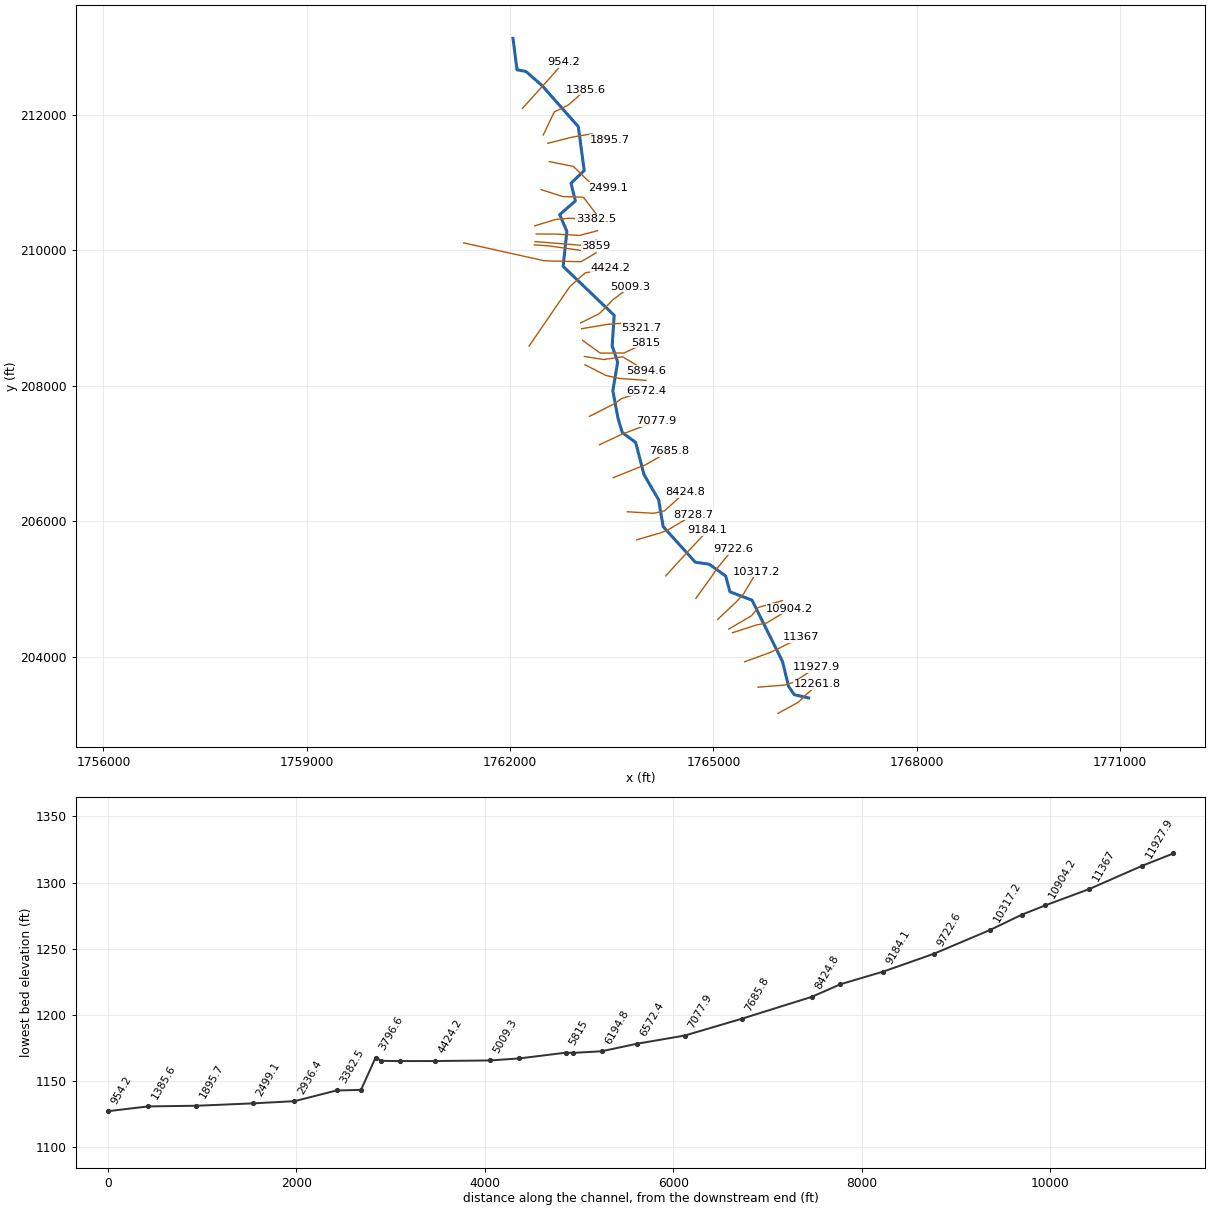
--- HorseCr.prj (project) ---

Proj Title=HorseCr
Current Plan=p01
Default Exp/Contr=0,0
English Units
Geom File=g01
Flow File=f01
Plan File=p01
BEGIN DESCRIPTION:
END DESCRIPTION:
DSS Export Rating Curves= 0
DSS Export Rating Curve Sorted= 0
DSS Export Volume Flow Curves= 0
DXF OffsetX= 0
DXF OffsetY= 0
DXF ScaleX= 0
DXF ScaleY= 0

--- HorseCr.p01 (plan) ---

Plan Title=Floodplain
Program Version=4.00
Geom File=g01
Flow File=f01
K Sum by GR=0
Std Step Tol=0.01
Critical Tol=0.01
Num of Std Step Trials=20
Max Error Tol=0.3
Flow Tol Ratio=0.001
Split Flow NTrial=30
Split Flow Tol=0.02
Split Flow Ratio=0.02
Log Output Level=0
Friction Slope Method=1
Unsteady Friction Slope Method=2
Unsteady Bridges Friction Slope Method=1
Global Log Level=0
CheckData=False
Run HTab=0
Run UNet=0
Run PostProcess=0
UNET Theta=0
UNET Theta Warmup=0
UNET ZTol=0
UNET ZSATol=0
UNET MxIter=0
UNET MaxInSteps=0
UNET DtIC=0
UNET DtMin=0
UNET MaxCRTS=0
UNET WFStab=0
UNET SFStab=0
UNET WFX=0
UNET SFX=0
UNET DSS MLevel=0
UNET DZMax Abort=0
UNET Convert EG Bridges=0
UNET Use Existing IB Tables=0
UNET Froude Limit=0
UNET Froude Power=0
Write IC File=0
Echo Input=False
Echo Output=False
Write Detailed=0

--- HorseCr.f01 (steady flow) ---

Flow Title=NFF Regression Equation
Program Version=4.00
Number of Profiles=1
Profile Names=P100yr
River Rch & RM=HorseCr,Main      ,12261.8
302.4802
River Rch & RM=HorseCr,Main      ,12261.8
303.1336
River Rch & RM=HorseCr,Main      ,11927.9
562.6065
River Rch & RM=HorseCr,Main      ,10652
606.2792
River Rch & RM=HorseCr,Main      ,10317.2
663.4284
River Rch & RM=HorseCr,Main      ,8728.7
695.2496
River Rch & RM=HorseCr,Main      ,8424.8
853.0501
River Rch & RM=HorseCr,Main      ,5321.7
928.2078
River Rch & RM=HorseCr,Main      ,4424.2
1013.512
River Rch & RM=HorseCr,Main      ,4059.8
1256.877
Boundary for River Rch & Prof#=HorseCr,Main      ,1
Up Type=0
Dn Type=3
Dn Slope=0.004459

--- HorseCr.g01 (geometry) ---

Geom Title=USGS 10m DEM
Program Version=4.00

River Reach=HorseCr         ,Main
Reach XY= 30
      1766404.08      203393.174     1766190.648      203442.342
     1766107.956      203565.261      1766018.56      203931.784
     1765569.346        204835.8     1765243.051      204959.836
     1765180.474      205192.266     1764940.223       205365.47
     1764732.378      205395.641     1764257.462       205921.96
     1764191.533      206315.301     1763974.748      206689.646
     1763852.946      207162.327     1763655.157      207308.713
     1763591.463      207521.028     1763515.477      207926.662
     1763586.993      208350.175     1763505.419      208587.074
     1763535.422      209038.294     1762782.123      209760.756
     1762837.825      210276.604     1762731.028      210523.611
     1762963.457       210725.87     1762898.645      210986.235
     1763093.081      211175.084     1763006.279      211821.763
     1762468.427      212431.096     1762233.329       212636.52
     1762102.215      212660.359     1762042.381      213124.795

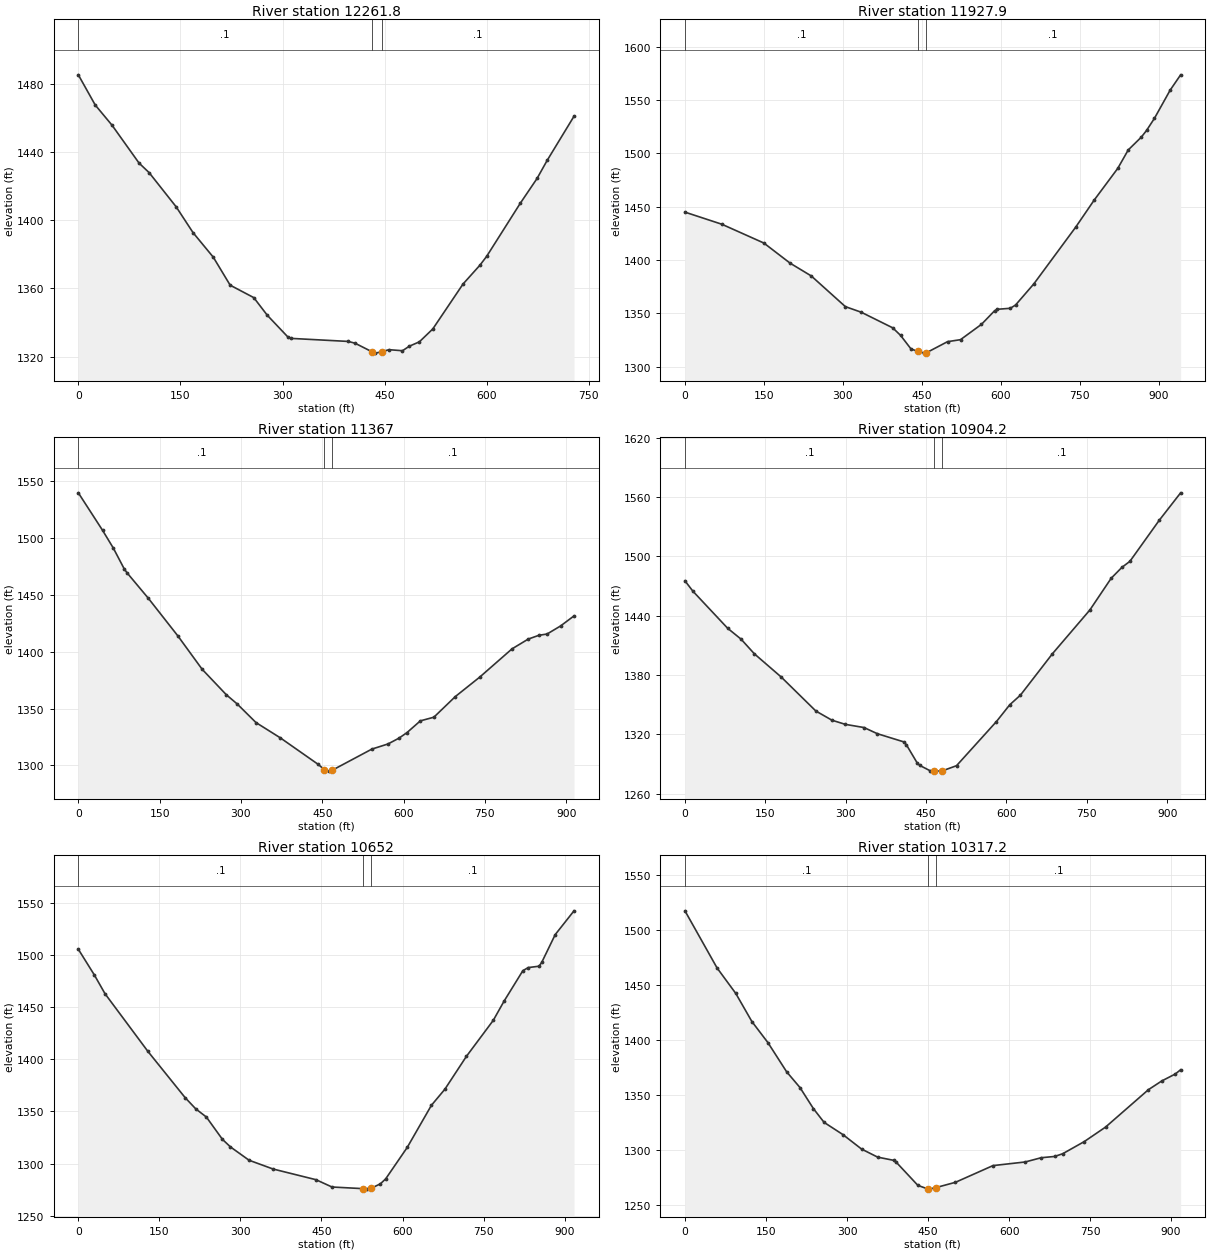
Type RM Length L Ch R = 1 ,12261.8 ,342.2,333.8,324.9
XS GIS Cut Line= 4
     1765951.888      203165.651     1766252.313      203329.275
     1766355.583      203429.863      1766533.96      203593.487
#Sta/Elev= 30
       0 1485.11    24.8 1467.44    49.6 1455.55    89.2 1433.41   104.1 1427.77
   143.8 1407.74   168.6 1392.62   198.3 1378.26   223.1 1361.85   257.8 1354.56
   277.6 1344.25   307.4 1331.71   312.4 1330.68   396.8 1328.89   406.7 1327.83
   431.1 1322.91   436.5 1322.04   446.1 1322.89   456.4 1324.05   476.3 1323.45
   486.3 1326.09   501.1 1328.66   520.8  1336.2   565.3 1362.56     590 1373.54
   599.9 1378.71   649.3 1409.81     674 1424.38   688.8 1434.93   728.3 1460.83
#Mann= 3 , 0 , 0
       0      .1       0   431.1    .045       0   446.1      .1       0
Bank Sta=431.1,446.1
XS Rating Curve= 0 ,0
Exp/Cntr=0.3,0.1

Type RM Length L Ch R = 1 ,11927.9 ,558.7,560.9,563.2
XS GIS Cut Line= 4
     1765657.737      203552.032      1766065.99      203584.907
     1766177.724       203624.91     1766525.194      203848.208
#Sta/Elev= 30
       0 1444.77    69.9 1433.45   149.8 1415.82   199.8  1396.9   239.8 1384.98
   304.7 1356.16   334.6 1350.99   394.6  1336.3   409.6 1329.16   429.4 1316.42
   442.3 1314.36   454.1  1312.6   457.3 1312.64   498.6 1323.34   523.3 1325.22
   563.1 1339.59     588  1352.3     593 1353.69   617.8 1354.63   627.8 1357.69
   662.6 1377.55   742.2 1430.81   777.1 1456.04   821.9 1485.78   841.8 1503.06
   866.6 1515.05   876.6 1521.35   891.5 1532.65   921.4 1559.12   941.3 1573.48
#Mann= 3 , 0 , 0
       0      .1       0   442.3    .045       0   457.3      .1       0
Bank Sta=442.3,457.3
XS Rating Curve= 0 ,0
Exp/Cntr=0.3,0.1

Type RM Length L Ch R = 1 ,11367   ,468.6,462.8,457
XS GIS Cut Line= 3
      1765460.09       203926.65     1765842.521       204066.33
     1766298.404      204288.537
#Sta/Elev= 30
       0  1539.4    44.7 1506.48    64.6 1490.83    84.4 1472.85    89.4 1469.43
   129.1 1446.82   183.7 1413.69   228.4 1384.45   273.1 1362.04   292.9 1354.06
   327.7 1337.67   372.4  1324.3     442  1301.1   453.7 1296.41   461.8 1295.02
   468.7  1295.9   541.4 1314.36   571.2 1318.87   591.1 1323.88     606 1328.75
   630.9 1339.17   655.8 1342.36   695.5 1360.53   740.3 1377.54   799.9 1402.36
   829.8 1410.95   849.7 1414.32   864.6 1415.41   889.4 1422.46   914.3 1431.32
#Mann= 3 , 0 , 0
       0      .1       0   453.7    .045       0   468.7      .1       0
Bank Sta=453.7,468.7
XS Rating Curve= 0 ,0
Exp/Cntr=0.3,0.1

Type RM Length L Ch R = 1 ,10904.2 ,236.3,252.2,262.5
XS GIS Cut Line= 4
     1765280.469       204354.96     1765631.467      204469.126
     1765785.964      204499.473     1766126.177      204707.219
#Sta/Elev= 30
       0 1475.37      15 1464.77    79.8  1427.3   104.7 1416.35   129.7 1401.42
   179.6 1378.04   244.4 1343.57   274.3 1334.32   299.3  1330.1   334.2 1326.88
   359.1 1320.64   408.5 1312.36   413.4 1309.39   433.1 1291.38     438 1288.63
   457.7 1283.12   464.6  1282.8   467.5 1282.76   479.6 1282.89   506.9 1288.25
   581.4 1332.93   606.3 1349.94   626.2 1359.67     686 1401.62   755.8 1445.85
   795.6 1477.98   815.6 1488.98   830.5 1495.08   885.3 1536.65   925.2 1564.42
#Mann= 3 , 0 , 0
       0      .1       0   464.6    .045       0   479.6      .1       0
Bank Sta=464.6,479.6
XS Rating Curve= 0 ,0
Exp/Cntr=0.3,0.1

Type RM Length L Ch R = 1 ,10652   ,335.8,334.8,339.4
XS GIS Cut Line= 4
     1765224.533      204408.431     1765561.116       204605.69
     1765661.815       204728.46      1766016.33      204829.159
#Sta/Elev= 30
       0 1505.46    29.6 1480.87    49.4 1462.85   128.4 1407.84   197.5 1363.38
   217.3 1352.54     237 1344.68   266.7 1323.32   281.5 1316.08     316  1303.3
   360.5 1294.88   439.8 1284.66   469.5 1277.65   527.3 1276.07     534 1275.62
   542.3 1276.54   558.9 1280.65   568.8 1285.42   608.7 1315.55   653.5 1355.94
   678.4 1371.34   718.2 1402.78     768 1437.35     788 1455.78   822.8 1484.97
   832.8  1487.9   852.7 1489.21   857.7  1492.9   882.6 1519.48   917.4 1542.27
#Mann= 3 , 0 , 0
       0      .1       0   527.3    .045       0   542.3      .1       0
Bank Sta=527.3,542.3
XS Rating Curve= 0 ,0
Exp/Cntr=0.3,0.1

Type RM Length L Ch R = 1 ,10317.2 ,591.3,594.6,597.8
XS GIS Cut Line= 4
     1765062.421      204551.638      1765329.37       204802.95
     1765443.864      204927.099     1765639.435       205255.31
#Sta/Elev= 30
       0 1517.37    59.4 1465.42    94.1  1442.2   123.9 1416.63   153.6 1397.43
   188.3 1370.84     213 1356.52   237.8 1337.38   257.6 1324.85   292.3 1313.78
     327 1300.56   356.7 1293.23   386.5  1290.3   391.5 1288.41   431.2 1267.52
   449.6 1264.25   451.1 1264.11   464.6  1265.5   500.8 1270.33   570.2 1285.52
   629.8 1288.82   659.6  1292.7   684.4 1293.84   699.3 1296.33     739 1307.31
   778.6 1320.56     858 1354.62   882.8 1362.59   907.6 1368.84   917.6 1372.74
#Mann= 3 , 0 , 0
       0      .1       0   449.6    .045       0   464.6      .1       0
Bank Sta=449.6,464.6
XS Rating Curve= 0 ,0
Exp/Cntr=0.3,0.1

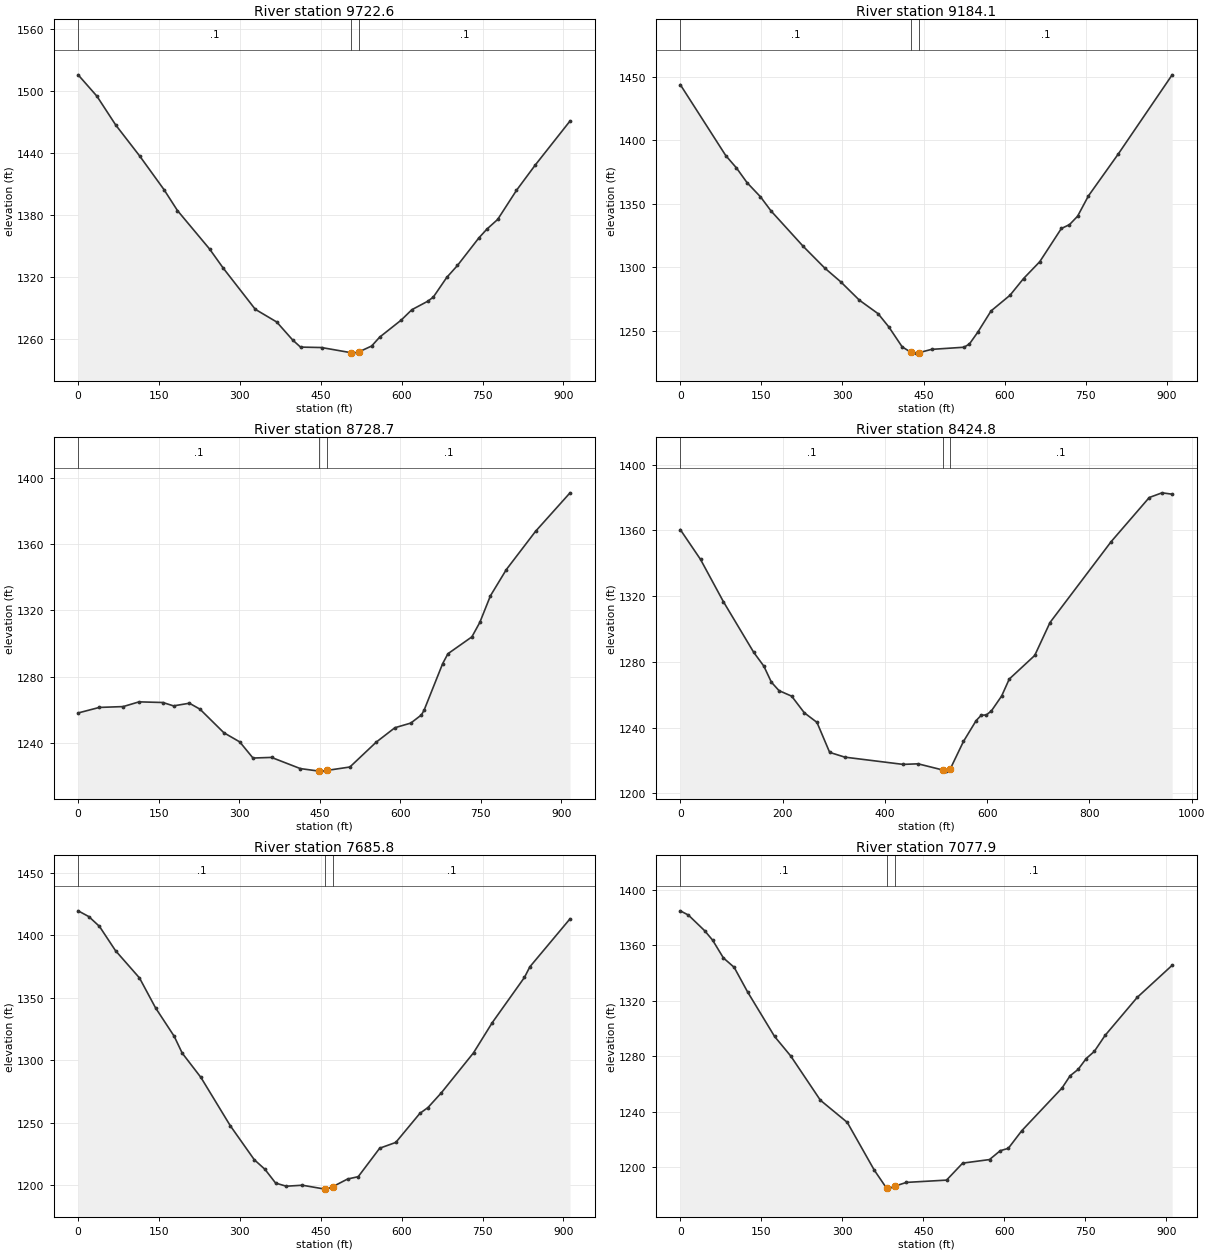
Type RM Length L Ch R = 1 ,9722.6  ,542.7,538.5,534.4
XS GIS Cut Line= 4
     1764741.154      204863.075      1764962.44       205169.88
     1765049.345      205299.547     1765289.846      205591.004
#Sta/Elev= 30
       0  1515.4    34.8 1494.76    69.7 1466.86   114.5 1436.62   159.3 1404.28
   184.2 1384.06   243.9 1346.78   268.8 1328.57   328.5 1288.54   368.3 1276.24
   397.8 1258.86   412.4 1251.96   451.4 1251.54   505.1 1246.63     510 1246.13
   520.1  1247.2   544.3 1253.02   559.2 1261.62     599 1278.04   618.9 1288.15
   648.7 1296.44   658.7 1300.38   683.5 1319.32   703.4 1330.92   743.2 1357.64
   758.1 1366.15     778 1375.47   812.8 1403.57   847.6 1428.04   912.2 1470.74
#Mann= 3 , 0 , 0
       0      .1       0   505.1    .045       0   520.1      .1       0
Bank Sta=505.1,520.1
XS Rating Curve= 0 ,0
Exp/Cntr=0.3,0.1

Type RM Length L Ch R = 1 ,9184.1  ,465.2,455.4,445.6
XS GIS Cut Line= 3
     1764296.748      205195.298     1764603.533      205531.368
      1764914.24      205863.753
#Sta/Elev= 30
       0 1443.84    84.1 1388.04   103.9 1378.31   123.6 1366.68   148.4 1355.56
   168.2 1344.32   227.5 1316.58   267.1 1299.59   296.8 1288.72   331.4 1274.23
     366 1263.62   385.8 1253.22   410.5 1237.53   426.3 1233.38   435.2  1232.6
   441.3 1232.94     465 1235.56     525 1237.24     535 1239.85     550 1248.85
     575 1265.83     610 1278.13     635 1291.25     665 1304.51     705 1330.66
     720 1333.67     735  1340.3     755 1356.25     810  1389.1     910 1451.54
#Mann= 3 , 0 , 0
       0      .1       0   426.3    .045       0   441.3      .1       0
Bank Sta=426.3,441.3
XS Rating Curve= 0 ,0
Exp/Cntr=0.3,0.1

Type RM Length L Ch R = 1 ,8728.7  ,307.8,303.9,299.9
XS GIS Cut Line= 4
     1763866.186      205726.043     1764221.682      205829.251
     1764355.488      205887.187     1764698.486      206094.017
#Sta/Elev= 30
       0 1258.06    39.5  1261.4    83.9  1261.9   113.5 1264.76   157.9 1264.36
   177.7 1262.33   207.3 1263.93     227 1260.35   271.5 1246.14   301.1 1240.62
   325.8 1230.88   360.3 1231.26   413.9 1224.53   448.6    1223   452.8 1222.99
   463.6 1223.42   506.3 1225.47   555.5  1240.5   590.2 1249.16   619.8 1251.96
   639.6 1256.87   644.6 1259.75   679.2 1287.82     689 1293.77   733.6 1303.93
   748.4 1312.65   768.2 1328.71   797.8  1344.5   852.2 1367.55   916.5 1390.78
#Mann= 3 , 0 , 0
       0      .1       0   448.6    .045       0   463.6      .1       0
Bank Sta=448.6,463.6
XS Rating Curve= 0 ,0
Exp/Cntr=0.3,0.1

Type RM Length L Ch R = 1 ,8424.8  ,735.9,739,742.1
XS GIS Cut Line= 4
     1763729.146      206140.003     1764119.604      206117.553
     1764278.239      206153.419     1764580.336      206427.927
#Sta/Elev= 30
       0 1360.53    39.6 1342.35    84.2  1316.7   143.6 1285.79   163.4 1277.39
   178.2  1267.6   193.1 1262.46   217.8 1259.11   242.6 1248.96   267.3 1243.14
   292.1 1224.88   321.8 1221.97   435.5 1217.57     465 1217.91     513 1214.17
   519.2 1213.46     528 1214.82   553.7  1231.5   578.6 1244.24   588.6 1247.52
   598.5 1247.64   608.5 1250.18   628.4 1259.18   643.3 1269.52   693.1 1283.88
     723 1303.94   842.5 1353.16   917.1 1380.05     942  1382.9   961.9 1382.07
#Mann= 3 , 0 , 0
       0      .1       0     513    .045       0     528      .1       0
Bank Sta=513,528
XS Rating Curve= 0 ,0
Exp/Cntr=0.3,0.1

Type RM Length L Ch R = 1 ,7685.8  ,609.1,607.9,604.9
XS GIS Cut Line= 4
     1763519.563      206641.968     1763896.135      206793.477
     1763988.557      206827.964     1764342.375      207030.657
#Sta/Elev= 30
       0 1419.54    19.8 1414.94    39.6 1407.07    69.3  1387.7   113.8 1365.85
   143.6 1341.93   178.2 1319.18     193 1305.76   227.7  1286.3   282.2 1247.66
   326.7 1220.48   346.5  1212.8   366.3 1201.78   386.1 1199.29   415.8 1200.08
   457.1 1197.02   460.2 1196.96   472.1 1198.91   499.6 1205.01   519.5 1206.93
   559.3 1229.69   589.1  1234.3   633.8 1257.55   648.8 1262.21   673.6 1273.98
   733.3 1305.98   768.1 1330.14   827.8 1366.31   837.7 1374.71   912.3 1413.16
#Mann= 3 , 0 , 0
       0      .1       0   457.1    .045       0   472.1      .1       0
Bank Sta=457.1,472.1
XS Rating Curve= 0 ,0
Exp/Cntr=0.3,0.1

Type RM Length L Ch R = 1 ,7077.9  ,500.4,505.5,512.4
XS GIS Cut Line= 4
     1763319.964      207129.302     1763645.078      207281.798
     1763811.989      207345.252     1764160.928       207477.13
#Sta/Elev= 30
       0  1384.8      15 1381.75    44.9 1370.56    59.8  1363.7    79.8 1350.87
    99.8 1344.05   124.7 1326.28   174.6 1294.22   204.5 1280.14   259.4 1248.26
   309.2 1232.28   359.1 1197.91   382.1 1184.76   383.9 1184.17   397.1 1186.29
   418.6 1189.02     493 1190.67   522.8 1202.91   572.5 1205.48   592.4 1211.87
   607.3 1213.57   632.2 1226.26   706.8 1257.08   721.7 1265.87   736.6 1270.49
   751.5 1278.29   766.5 1283.43   786.4 1294.94     846 1322.41   910.7 1345.54
#Mann= 3 , 0 , 0
       0      .1       0   382.1    .045       0   397.1      .1       0
Bank Sta=382.1,397.1
XS Rating Curve= 0 ,0
Exp/Cntr=0.3,0.1

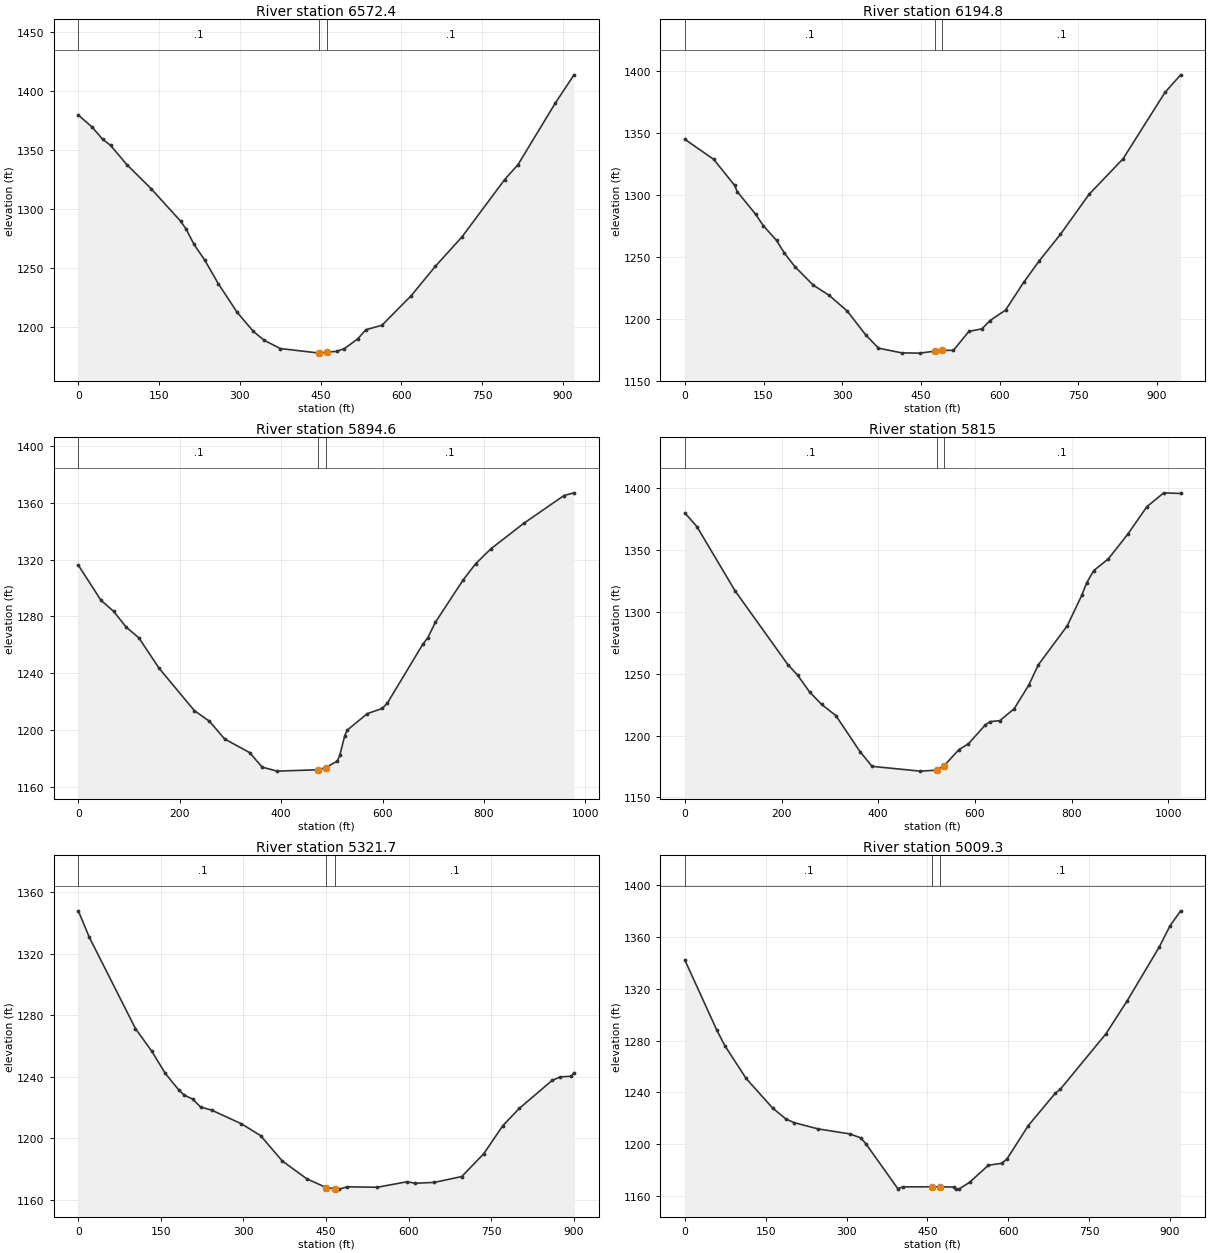
Type RM Length L Ch R = 1 ,6572.4  ,396.2,377.6,359
XS GIS Cut Line= 4
     1763171.176      207547.673     1763527.825      207728.736
     1763650.595      207812.882     1764004.883      207924.878
#Sta/Elev= 30
       0 1379.76      25 1369.85      45 1359.38      60    1354      90 1337.81
     135 1317.45     190 1289.78     200  1283.2     215 1270.07     235 1256.61
     260 1236.77     295 1212.49     325 1196.41     345 1188.89     375 1181.87
   447.4    1178   449.6 1177.98   462.4 1178.96   479.4 1179.43   494.2 1181.86
     519 1190.17   533.9 1197.81   563.7  1201.6   618.2 1226.76   662.8 1251.53
   712.3 1276.47   791.6 1325.12   816.4 1337.78   885.7 1389.97   920.4 1413.88
#Mann= 3 , 0 , 0
       0      .1       0   447.4    .045       0   462.4      .1       0
Bank Sta=447.4,462.4
XS Rating Curve= 0 ,0
Exp/Cntr=0.3,0.1

Type RM Length L Ch R = 1 ,6194.8  ,292.8,300.2,308.4
XS GIS Cut Line= 4
     1763104.073      208309.333     1763410.573      208152.223
     1763607.833      208108.081     1764005.592      208078.601
#Sta/Elev= 30
       0 1344.54    54.9 1328.46    94.8 1307.47    99.8 1302.43   134.8 1284.24
   149.8 1274.82   174.7  1263.1   189.7 1252.93   209.6 1242.03   244.6  1227.1
   274.5 1219.04   309.5 1206.19   344.4 1187.18   369.1 1176.28   413.4 1172.46
     448 1172.25   476.1 1173.83   491.1 1174.54     512 1174.47   541.6 1189.76
   566.5 1191.83   581.5 1198.42   611.4 1206.88   646.3 1229.46   676.2 1246.89
   716.1 1267.96   770.9  1300.3   835.7 1328.97   915.5 1382.37   945.4 1396.58
#Mann= 3 , 0 , 0
       0      .1       0   476.1    .045       0   491.1      .1       0
Bank Sta=476.1,491.1
XS Rating Curve= 0 ,0
Exp/Cntr=0.3,0.1

Type RM Length L Ch R = 1 ,5894.6  ,82,79.7,76.5
XS GIS Cut Line= 4
     1763096.296      208430.988     1763381.302      208386.156
     1763659.903      208426.185     1764010.557      208218.034
#Sta/Elev= 30
       0 1316.13    44.8 1291.36    69.6 1283.65    94.5 1272.45   119.4 1264.96
   159.2  1243.6   228.8 1213.71   258.7 1206.17   288.5 1193.73   337.9  1184.1
   362.6 1173.88   392.2 1171.05   473.3 1172.02   488.3 1173.59   510.7 1178.12
   515.7 1182.12   525.5 1195.99   530.5 1199.97     570 1211.56   599.8 1215.27
   609.8  1219.1   679.4 1260.41   689.3 1265.02   704.2 1275.85   758.9 1305.68
   783.8 1317.21   813.6 1327.62   878.3 1345.54   957.9  1365.2   977.8 1367.12
#Mann= 3 , 0 , 0
       0      .1       0   473.3    .045       0   488.3      .1       0
Bank Sta=473.3,488.3
XS Rating Curve= 0 ,0
Exp/Cntr=0.3,0.1

Type RM Length L Ch R = 1 ,5815    ,499.5,493.3,485.8
XS GIS Cut Line= 4
      1763068.93      208669.008     1763330.566      208480.529
     1763679.564      208481.909     1764000.839      208631.496
#Sta/Elev= 30
       0 1380.01    24.8 1369.03   104.2  1316.8   213.3 1257.23   233.2 1248.86
     258 1235.22   282.8 1225.19   312.5 1216.06   362.3 1186.97   387.3 1175.05
     487 1171.18   520.7 1171.93   535.7  1175.3   566.8  1188.5   586.7 1193.33
   621.6 1208.55   631.6 1211.27   651.5 1211.98   681.4 1221.69   711.4 1240.69
   731.4 1257.24   791.2 1288.78   821.2 1313.44   831.2 1323.42   846.2  1333.5
   876.1 1342.87     916 1362.66     956 1385.14   990.9 1396.35  1025.8 1395.83
#Mann= 3 , 0 , 0
       0      .1       0   520.7    .045       0   535.7      .1       0
Bank Sta=520.7,535.7
XS Rating Curve= 0 ,0
Exp/Cntr=0.3,0.1

Type RM Length L Ch R = 1 ,5321.7  ,296.1,312.4,328.7
XS GIS Cut Line= 4
     1763054.679      208840.562     1763439.541      208905.396
     1763640.939       208920.57     1763941.657      208852.977
#Sta/Elev= 30
       0 1347.89    19.8 1330.79   103.8 1271.28   133.4 1256.59   158.1 1242.07
   182.8 1231.24   192.7 1227.95   207.5 1225.48   222.3 1220.22   242.1 1218.26
   296.4 1209.33     331 1201.68   370.5 1185.17   414.9 1173.59   450.5 1167.83
   465.5 1167.16     474 1166.85   488.8 1168.35     543 1168.07   597.2 1171.64
   612.1 1170.66   646.9 1171.24   696.6 1175.05   736.4 1189.83   771.2 1208.17
     801 1219.34   860.7 1237.58   875.6 1239.85   895.5 1240.29   900.5 1242.56
#Mann= 3 , 0 , 0
       0      .1       0   450.5    .045       0   465.5      .1       0
Bank Sta=450.5,465.5
XS Rating Curve= 0 ,0
Exp/Cntr=0.3,0.1

Type RM Length L Ch R = 1 ,5009.3  ,586.5,585.1,583.6
XS GIS Cut Line= 4
     1763039.533      208925.751     1763318.151      209064.031
     1763522.308      209272.326      1763776.93      209461.624
#Sta/Elev= 30
       0 1342.15    59.2  1288.1    74.1 1276.14   113.6 1250.79   162.9 1227.87
   187.6 1219.46   202.4  1216.7   246.9 1211.85   306.1 1207.95   325.9 1204.97
   335.8 1200.41   395.1 1165.66     405 1167.05   458.4  1167.1   473.4  1167.1
   498.9 1166.92   503.8  1165.3   508.8  1165.4   528.6 1170.63   563.2 1183.77
   587.9 1185.23   597.8 1188.67   637.4 1214.44     687 1239.22   696.9 1242.57
   781.2 1285.21   820.8 1310.78   880.3 1352.34   900.2 1368.65     920 1380.29
#Mann= 3 , 0 , 0
       0      .1       0   458.4    .045       0   473.4      .1       0
Bank Sta=458.4,473.4
XS Rating Curve= 0 ,0
Exp/Cntr=0.3,0.1

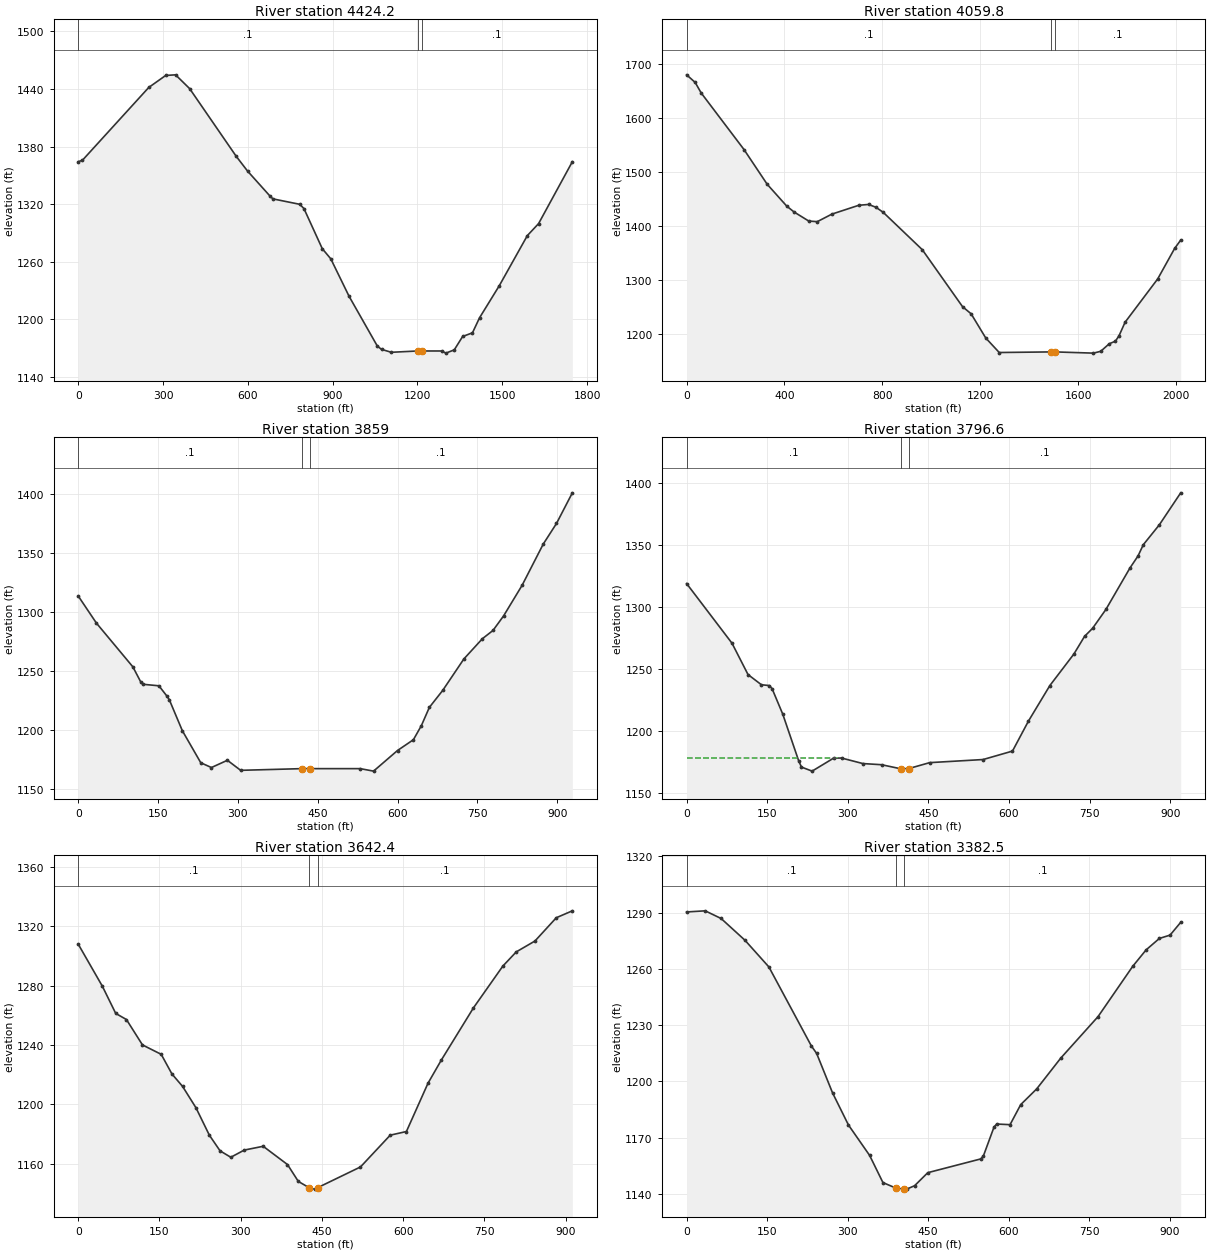
Type RM Length L Ch R = 1 ,4424.2  ,382.6,364.5,346.4
XS GIS Cut Line= 4
     1762279.707      208584.699     1762880.869      209461.309
     1763105.718      209662.707     1763480.925      209739.955
#Sta/Elev= 30
       0 1364.16      15 1365.74   249.5  1441.5   309.4 1453.98   344.3 1454.63
   394.2 1440.22   558.9 1369.76   598.8 1354.47   678.7 1328.27   688.7 1325.46
   783.5 1319.82   798.4 1315.41   863.3 1273.59   893.3 1263.09   958.1 1224.01
    1058 1172.22  1072.8 1168.78  1107.5 1165.74  1201.3  1167.1  1216.3  1167.1
  1285.6  1167.1  1300.5 1164.86  1330.2 1168.27  1359.8  1182.2  1394.6 1186.01
  1419.5 1201.61  1489.2 1234.94  1588.7 1287.24  1628.5 1299.74  1747.9 1364.18
#Mann= 3 , 0 , 0
       0      .1       0  1201.3    .045       0  1216.3      .1       0
Bank Sta=1201.3,1216.3
XS Rating Curve= 0 ,0
Exp/Cntr=0.3,0.1

Type RM Length L Ch R = 1 ,4059.8  ,203.8,200.7,197.7
XS GIS Cut Line= 4
     1761314.774      210107.116     1762508.243      209842.264
     1763047.756      209829.185     1763268.464      209960.758
#Sta/Elev= 30
       0 1679.14    34.9 1665.14    59.9 1645.42   234.5 1541.09   329.3 1476.88
   409.2 1436.51   439.1 1425.68     499 1408.94   533.9 1407.78   593.8 1421.76
   703.6 1438.06   743.5  1439.6   773.4 1434.45   803.4 1425.04     963 1356.04
  1127.7 1250.62  1162.6 1237.55  1222.5 1192.74  1277.5 1165.98  1490.2  1167.1
  1505.2  1167.1  1662.2 1164.84  1692.2 1168.19  1727.2 1182.21  1752.2 1186.91
  1767.1 1196.96  1791.8 1221.94  1925.2 1302.06  1994.4 1358.42  2019.1 1373.71
#Mann= 3 , 0 , 0
       0      .1       0  1490.2    .045       0  1505.2      .1       0
Bank Sta=1490.2,1505.2
XS Rating Curve= 0 ,0
Exp/Cntr=0.3,0.1

Type RM Length L Ch R = 1 ,3859    ,60.6,62.4,64.2
XS GIS Cut Line= 4
     1762358.163      210076.977     1762563.111      210064.168
     1763062.672      209993.717     1763269.221      210065.769
#Sta/Elev= 30
       0  1313.6    34.2  1290.6   102.7 1253.46   117.3 1240.83   122.2 1238.68
   151.6 1237.41   166.2 1228.94   171.1 1225.64   195.6 1199.33   230.3 1172.09
   250.3 1168.04   280.3  1174.2   305.2 1165.67   420.1  1167.1   435.1  1167.1
     530  1167.1     555 1164.99     600 1182.49   629.9 1191.66   644.9 1203.63
   659.9 1219.12   684.9 1233.46   724.8 1260.23   759.6  1277.4   779.5 1284.41
   799.3 1296.68   834.1 1322.64   873.9 1357.69   898.8  1375.2   928.6 1401.19
#Mann= 3 , 0 , 0
       0      .1       0   420.1    .045       0   435.1      .1       0
#XS Ineff= 2 , 0
          279.01 1173.75
Permanent Ineff=
       F       F
Bank Sta=420.1,435.1
XS Rating Curve= 0 ,0
Exp/Cntr=0.3,0.1

Type RM Length L Ch R = 1 ,3796.6  ,151.4,154.2,155.6
XS GIS Cut Line= 3
     1762367.293      210126.052     1763051.145      210071.273
     1763272.028      210147.257
#Sta/Elev= 30
       0 1318.73    84.5 1270.59   114.3 1245.32   139.2  1237.1   154.1 1236.44
   159.1 1233.93     179 1213.33   208.8 1175.46   213.8 1170.68   233.6 1167.42
   273.4 1177.85   288.3 1177.99   328.1 1173.52   362.9 1172.59   398.4 1169.32
   413.4 1169.48   452.4 1174.27   551.8 1176.77   606.5 1183.59   636.3 1207.85
   676.1 1236.47   720.8 1261.89   740.7 1276.17   755.6 1282.63   780.5 1297.93
   825.2 1331.34   840.1 1340.94     850 1350.08   879.9 1366.16   919.6 1391.92
#Mann= 3 , 0 , 0
       0      .1       0   398.4    .045       0   413.4      .1       0
#XS Ineff= 2 , 0
          285.21 1178.03
Permanent Ineff=
       F       F
Bank Sta=398.4,413.4
XS Rating Curve= 0 ,0
Exp/Cntr=0.3,0.1

Type RM Length L Ch R = 1 ,3642.4  ,260,259.9,273.6
XS GIS Cut Line= 4
     1762385.743      210238.369      1762672.35      210236.768
     1763026.205      210217.554     1763288.795      210286.404
#Sta/Elev= 30
       0 1307.89    44.5 1279.62    69.2  1261.3      89 1257.17   118.6 1240.09
   153.2 1233.76     173 1220.55   192.7 1212.14   217.4 1197.77   242.1 1179.34
   261.9 1168.78   281.7 1164.47   306.6 1169.31   341.5 1171.86   386.4 1159.56
   406.4 1148.21   426.9 1143.85   436.4 1143.02   441.9 1143.97   521.2 1157.96
   576.1 1179.34     606  1181.8   645.9 1214.34   670.6 1229.98   729.8 1265.05
   784.1 1293.17   808.8 1302.71   843.4 1310.04   882.8 1325.71   912.4 1330.35
#Mann= 3 , 0 , 0
       0      .1       0   426.9    .045       0   441.9      .1       0
Bank Sta=426.9,441.9
XS Rating Curve= 0 ,0
Exp/Cntr=0.3,0.1

Type RM Length L Ch R = 1 ,3382.5  ,448.8,446.1,443.4
XS GIS Cut Line= 4
     1762362.939      210358.112     1762675.001      210453.712
     1762871.188      210470.061     1763268.285      210452.262
#Sta/Elev= 30
       0 1290.32    34.6 1290.92    64.3 1286.83   108.8 1275.22   153.3 1261.01
   232.4 1218.93   242.3 1214.91     272 1193.84   301.6 1176.75   341.1 1160.51
   365.8 1146.08   390.4 1143.06   405.4 1142.65     410 1142.57   424.8 1144.38
   449.4 1151.34   548.1 1158.67   553.1 1160.31   572.9 1175.71   577.9 1177.27
   602.7 1176.93   622.6 1187.63   652.4 1196.02   697.2 1212.42   766.7 1234.54
   831.3 1261.35   856.2  1270.1     881 1276.21   900.9 1277.98   920.7 1284.79
#Mann= 3 , 0 , 0
       0      .1       0   390.4    .045       0   405.4      .1       0
Bank Sta=390.4,405.4
XS Rating Curve= 0 ,0
Exp/Cntr=0.3,0.1

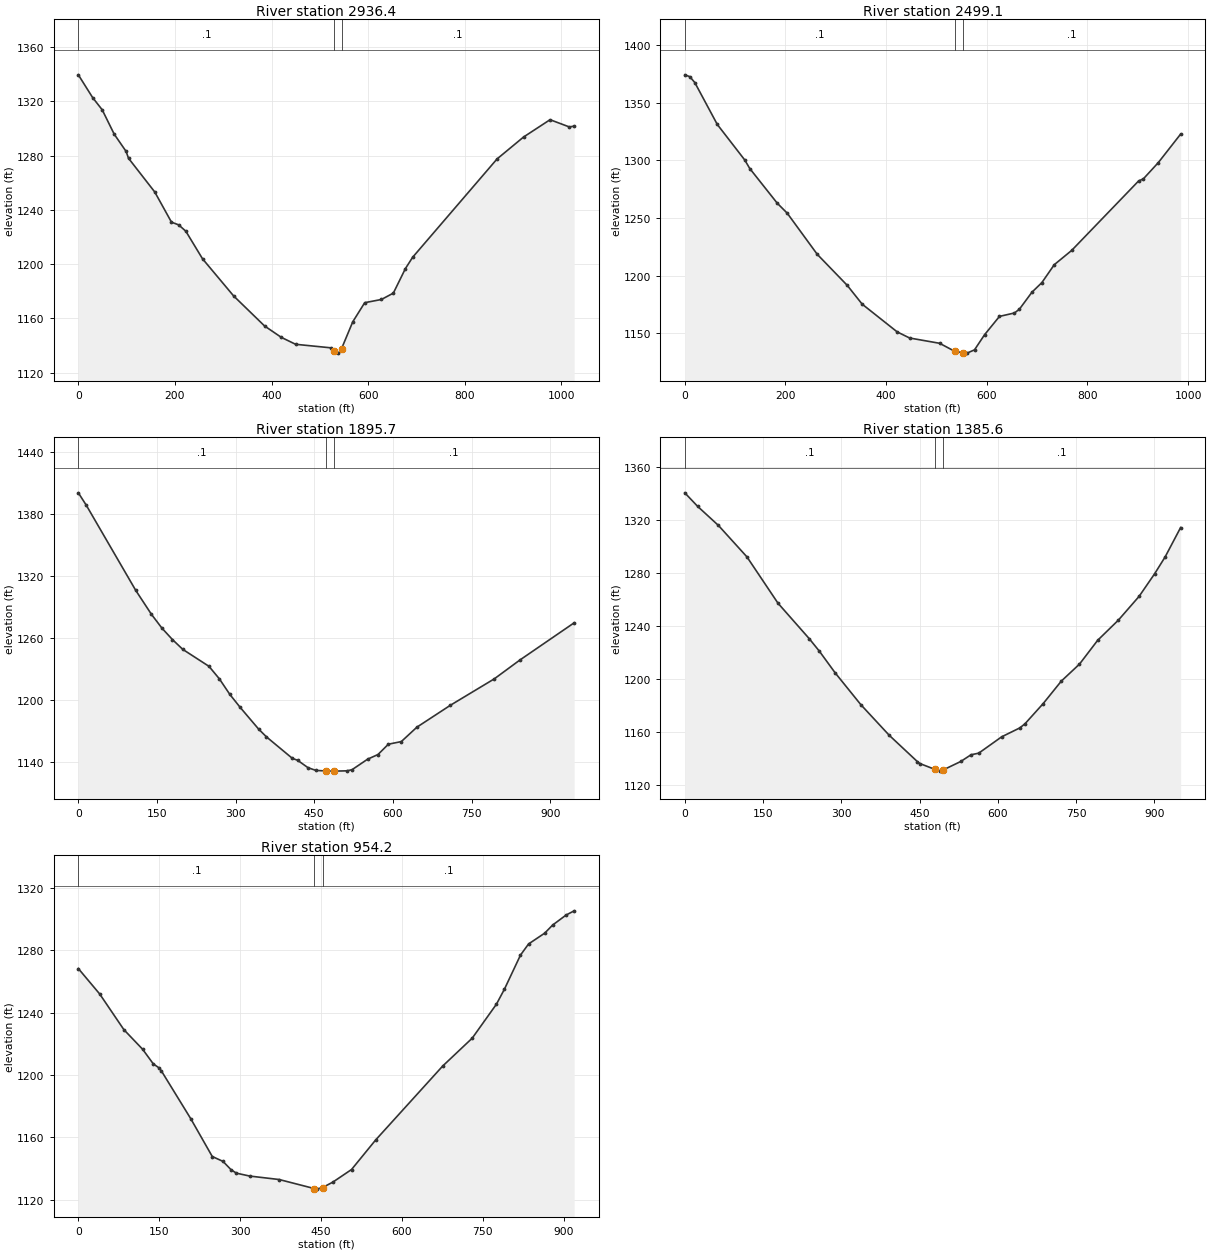
Type RM Length L Ch R = 1 ,2936.4  ,454.9,437.3,419.7
XS GIS Cut Line= 4
     1762459.074      210892.451     1762779.634      210790.499
     1763080.454       210780.69     1763317.692      210471.968
#Sta/Elev= 30
       0 1339.48    29.7 1322.67    49.5 1313.68    74.2 1295.81    98.9 1283.07
   103.9 1278.03   158.3 1253.15   192.9 1230.94   207.8 1228.95   222.6 1224.27
   257.2 1203.94   321.5 1176.63   385.7 1154.46   420.3 1146.09   449.9 1140.98
   523.9 1138.34     530 1136.15   538.7 1134.47     545 1137.71   568.3 1157.57
     593 1171.63   627.5 1173.98   652.3 1178.68   677.3 1196.76   692.3 1205.11
     867  1277.5   921.9 1293.65   976.8 1306.42  1016.7 1301.09  1026.7 1301.69
#Mann= 3 , 0 , 0
       0      .1       0     530    .045       0     545      .1       0
Bank Sta=530,545
XS Rating Curve= 0 ,0
Exp/Cntr=0.3,0.1

Type RM Length L Ch R = 1 ,2499.1  ,582.7,603.5,624.4
XS GIS Cut Line= 4
     1762577.898      211306.261     1762933.314      211235.189
     1763178.547      210996.495     1763448.077      210918.503
#Sta/Elev= 30
       0 1374.17     9.9 1372.58    19.9 1367.46    64.6 1331.11   119.2 1300.29
   129.1 1292.93   183.7 1262.86   203.6 1254.16   263.2 1218.52   322.7 1191.65
   352.5 1175.29     422 1151.26   446.8 1145.94   506.3 1141.37   537.1 1134.25
   552.1  1133.3   560.8 1132.83   575.7 1135.66   595.6 1148.73   625.3 1164.68
   655.1 1167.65     665 1170.96   689.8 1185.63   709.6    1194   734.2 1209.52
   768.7 1221.86   901.6 1282.04   911.4 1284.02     941 1298.07   985.3 1322.76
#Mann= 3 , 0 , 0
       0      .1       0   537.1    .045       0   552.1      .1       0
Bank Sta=537.1,552.1
XS Rating Curve= 0 ,0
Exp/Cntr=0.3,0.1

Type RM Length L Ch R = 1 ,1895.7  ,503.8,510,516.3
XS GIS Cut Line= 4
     1762556.268      211576.173     1762913.695      211666.799
     1763201.435      211715.846     1763473.819      211631.488
#Sta/Elev= 30
       0 1400.67      15  1388.8   109.6 1306.07   139.5 1282.91   159.4 1269.61
   179.4 1258.54   199.3 1248.96   249.2 1232.56   269.1 1220.39     289 1205.34
   308.9 1192.67   343.8 1171.81   358.8 1164.22   408.3 1143.36   418.2 1141.54
     438 1134.39   452.8 1131.75     472 1131.14     487 1131.01   512.2 1131.29
   522.1 1132.39   551.8 1142.58   571.6  1147.1   591.4  1157.1   616.1 1159.64
   645.8 1173.59   709.8 1194.86   793.4  1220.4   842.5 1238.75   945.8 1274.72
#Mann= 3 , 0 , 0
       0      .1       0     472    .045       0     487      .1       0
Bank Sta=472,487
XS Rating Curve= 0 ,0
Exp/Cntr=0.3,0.1

Type RM Length L Ch R = 1 ,1385.6  ,422.7,431.4,440.1
XS GIS Cut Line= 4
     1762489.623       211699.23     1762652.113      212039.554
     1762854.839      212137.647     1763116.403      212367.045
#Sta/Elev= 30
       0 1340.34    24.8 1330.06    64.5 1315.73   119.1 1292.04   178.6 1257.12
   238.2 1230.51     258 1220.89   287.8  1204.8   337.4 1180.61   391.8 1157.53
   445.7  1137.7   450.6 1136.22   479.5 1131.81   489.7 1130.52   494.5 1131.31
   528.9  1137.8   548.5 1142.85   563.2 1144.05   607.3  1156.4   642.1 1163.12
     652 1166.25   686.8 1181.44   721.6 1198.41   756.4  1211.2   791.2 1229.14
     831  1244.4   870.7 1262.32   900.5 1279.39   920.4 1291.94   950.2 1314.18
#Mann= 3 , 0 , 0
       0      .1       0   479.5    .045       0   494.5      .1       0
Bank Sta=479.5,494.5
XS Rating Curve= 0 ,0
Exp/Cntr=0.3,0.1

Type RM Length L Ch R = 1 ,954.2   ,975.9,954.2,932.1
XS GIS Cut Line= 3
     1762180.407      212089.945     1762589.987      212543.099
     1762793.213      212775.061
#Sta/Elev= 30
       0 1268.41    39.7 1252.04    84.4 1229.21   119.2 1216.61     139 1207.22
     149 1204.82     154 1202.71   208.6 1171.95   248.3 1147.79   268.2 1144.66
   283.1 1139.33     293 1137.11   317.8 1135.24   372.4 1133.02   437.7  1127.2
     442 1126.86   452.7 1127.87   471.8 1131.35   506.5 1139.45   551.2 1158.41
   675.5 1205.86   730.2 1223.73     775 1245.48   789.9 1255.14   819.7 1277.05
   834.7 1284.19   864.5  1291.1   879.4 1296.35   904.3 1302.75   919.2 1305.45
#Mann= 3 , 0 , 0
       0      .1       0   437.7    .045       0   452.7      .1       0
Bank Sta=437.7,452.7
XS Rating Curve= 0 ,0
Exp/Cntr=0.3,0.1

Chan Stop Cuts=-1
Use User Specified Reach Order=0